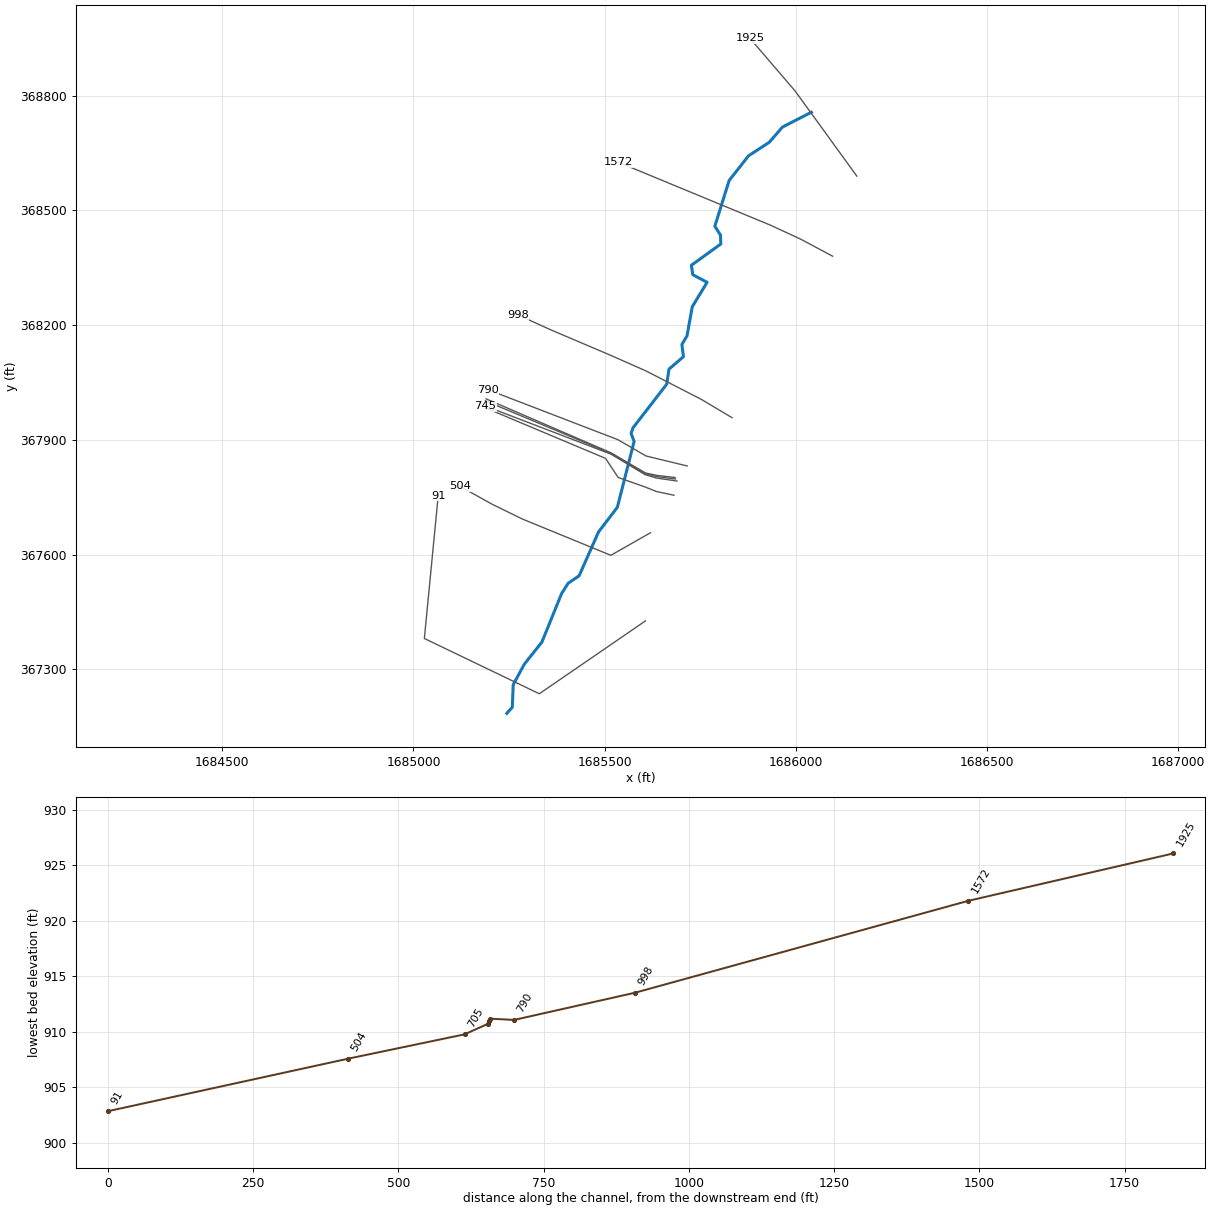
--- GLADEFK.prj (project) ---

Proj Title=GLADEFK
Current Plan=p01
Default Exp/Contr=0,0
English Units
Geom File=g01
Flow File=f01
Plan File=p01
BEGIN DESCRIPTION:
---------- MODELED AS PART OF WVEMD CTP PROGRAM, 2023----------
Stream Name: Glade Fork
Flood Zone:  AFH
Wetzel County, WV
HEC-RAS Version: RAS 6.3
Vertical Datum: NAVD88
Projection: NAD 1983 StatePlane West Virginia S FIPS 4702 (US Feet)
Terrain: 1-meter West Virginia FEMA R3 South Central (collected 2018-2020)
Land Use: 2019 NLCD
Hydrologic Method:
WV 2010 Regional Regression Equations
Additional Model Notes:
None
END DESCRIPTION:
DSS Export Rating Curves= 0
DSS Export Rating Curve Sorted= 0
DSS Export Volume Flow Curves= 0
DXF OffsetX= 0
DXF OffsetY= 0
DXF ScaleX= 0
DXF ScaleY= 0

--- GLADEFK.p01 (plan) ---

Plan Title=Floodplain
Program Version=6.30
Short Identifier=Floodplain
Geom File=g01
Flow File=f01
Subcritical Flow
K Sum by GR= 0
Std Step Tol= 0.01
Critical Tol= 0.01
Num of Std Step Trials= 20
Max Error Tol= 0.3
Flow Tol Ratio= 0.001
Split Flow NTrial= 30
Split Flow Tol= 0.02
Split Flow Ratio= 0.02
Log Output Level= 0
Friction Slope Method= 1
Unsteady Friction Slope Method= 2
Unsteady Bridges Friction Slope Method= 1
Parabolic Critical Depth
Global Vel Dist= 0 , 0 , 0
Global Log Level= 0
CheckData=False
Encroach Param=-1 ,0,0, 0
Mapping Interval=1HOUR
Computation Time Step Use Courant=        0
Computation Time Step Use Time Series=    0
Computation Time Step Count To Double=0
Computation Time Step Max Doubling=0
Computation Time Step Max Halving=0
Computation Time Step Residence Courant=0
Run HTab= 0
Run UNet= 0
Run Sediment= 0
Run PostProcess= 0
Run WQNet= 0
Run RASMapper=-1
UNET Theta= 0
UNET Theta Warmup= 0
UNET ZTol= 0
UNET ZSATol= 0
UNET MxIter= 0
UNET Max Iter WO Improvement= 0
UNET MaxInSteps= 0
UNET DtIC= 0
UNET DtMin= 0
UNET MaxCRTS= 0
UNET WFStab= 0
UNET SFStab= 0
UNET WFX= 1
UNET SFX= 1
UNET Gravity=32.17405
UNET 1D Methodology=Finite Difference
UNET DSS MLevel= 1
UNET Pardiso=0
UNET DZMax Abort= 0
UNET Use Existing IB Tables= 0
UNET Froude Reduction=False
UNET Froude Limit= 0
UNET Froude Power= 0
UNET D1 Cores= 0
UNET WindReference=Eulerian
UNET WindDragFormulation=Hsu (1988)
UNET D2 Coriolis=0
UNET D2 Cores= 0
UNET D2 Theta= 1
UNET D2 Theta Warmup= 1
UNET D2 Z Tol= 0.01
UNET D2 Volume Tol= 0.01
UNET D2 Max Iterations= 20
UNET D2 Equation= 0
UNET D2 RampUpFraction=0.1
UNET D2 TimeSlices= 1
UNET D2 Turbulence Formulation=Non-Conservative (original)
UNET D2 Eddy Viscosity=0.3
UNET D2 Transverse Eddy Viscosity=0.1
UNET D2 Smagorinsky Mixing=0
UNET D2 BCVolumeCheck=0
UNET D2 Cores=0
UNET D2 SolverType=PARDISO (Direct)
UNET D2 Minimum Iterations= 3
UNET D2 Maximum Iterations= 30
UNET D2 Restart Number= 10
UNET D2 Relaxation Coeff=1.3
UNET D2 SOR Precondition Iterations= 10
UNET D2 ILUT Maximum Fill= 8
UNET D2 ILUT Tolerance=1E-08
UNET D2 Convergence Tolerance=0.00001
UNET D1D2 MaxIter= 0
UNET D1D2 ZTol=0.01
UNET D1D2 QTol=0.1
UNET D1D2 MinQTol=1
Write IC File= 0
Write IC File at Fixed DateTime=0
Write IC File at Sim End=0
Echo Input=False
Echo Parameters=False
Echo Output=False
Write Detailed= 0
HDF Write Warmup=0
HDF Write Time Slices=0
HDF Flush=0
HDF Compression= 1
HDF Chunk Size= 1
HDF Spatial Parts= 1
HDF Use Max Rows=0
HDF Fixed Rows= 1
Calibration Method= 0
Calibration Iterations= 20
Calibration Max Change=0.05
Calibration Tolerance=0.2
Calibration Maximum=1.5
Calibration Minimum=0.5
Calibration Optimization Method= 1
WQ AD Non Conservative
WQ ULTIMATE=-1
WQ Max Comp Step=1HOUR
WQ Output Interval=15MIN
WQ Output Selected Increments= 0
WQ Output face flow=0
WQ Output face velocity=0
WQ Output face area=0
WQ Output face dispersion=0
WQ Output cell volume=0
WQ Output cell surface area=0
WQ Output cell continuity=0
WQ Output cumulative cell continuity=0
WQ Output face conc=0
WQ Output face dconc_dx=0
WQ Output face courant=0
WQ Output face peclet=0
WQ Output face adv mass=0
WQ Output face disp mass=0
WQ Output cell mass=0
WQ Output cell source sink temp=0
WQ Output nsm pathways=0
WQ Output nsm derived pathways=0
WQ Create Restart=0
WQ Fixed Restart=0
WQ System Summary=0
WQ Write To DSS=0
Sorting and Armoring Iterations= 10
XS Update Threshold= 0.02
Bed Roughness Predictor= 0
Hydraulics Update Threshold= 0.02
Energy Slope Method= 1
Volume Change Method= 1
Sediment Retention Method= 0
Sediment TS Multiplier= 1
Warm Up Method= 0
XS Weighting Method= 0
Number of US Weighted Cross Sections= 1
Number of DS Weighted Cross Sections= 1
Upstream XS Weight=0
Main XS Weight=1
Downstream XS Weight=0
Number of DS XS's Weighted with US Boundary= 1
Upstream Boundary Weight= 1
Weight of XSs Associated with US Boundary= 0
Number of US XS's Weighted with DS Boundary= 1
Downstream Boundary Weight= 0.5
Weight of XSs Associated with DS Boundary= 0.5
Percentile Method= 0
Sediment Output Level= 3
Mass or Volume Output= 0
Output Increment Type= 1
Profile and TS Output Increment= 1
Transport Output Increment 1
XS Output Flag= 0
XS Output Increment= 10
Read HDF5 Sediment Hotstart= 0
Sediment Hotstart Type= 0
Write Gradation File= 0
Read Gradation Hotstart= 0
Write HDF5 File= 1
Write Binary Output= 1
Write DSS Sediment File= 0
DSS Sediment Output Type= 1
SV Curve= 0
Specific Gage Flag= 0
Subcell Erosion Methods= 0
Subcell Deposition Methods= 0
Advection Scheme= 1
Matrix Solver= 0
Implicit Weighting Factor= 1
Maximum Outer Loop Convergence Iterations= 5
Convergence Maximum Absolute= 0.001
Convergence RMSE= 0.0001
Grain Fractions Max Abs Error= 0.001
Max Subgrid Regions= 1
Max Subgrid Length Scale= 3.402823E+38
Initial Layer Thickness= 3.402823E+38
Min Layer Thickness= 3.402823E+38
Max Layer Thickness= 3.402823E+38
Number of Layers= 5

--- GLADEFK.f01 (steady flow) ---

Flow Title=Flow
Program Version=6.31
Number of Profiles= 1
Profile Names=F01pct
River Rch & RM=GLADEFK,Main,1925
     572
Boundary for River Rch & Prof#=GLADEFK,Main            , 1
Up Type= 0
Dn Type= 3
Dn Slope=0.0113
DSS Import GetInterval= 0
DSS Import GetPeak= 0
DSS Import FillOption= 0

--- GLADEFK.g01 (geometry) ---

Geom Title=Geometry
Program Version=6.30

River Reach=GLADEFK         ,Main
Reach XY= 30
     1686040.628      368756.8571685965.15560217368718.182226057
1685930.32798618368678.1262744311685876.44650741368643.105853897
1685825.67416191368578.4222931971685788.19677889368458.918939803
1685803.04630801368435.5839654711685803.75342845 368412.24899114
 1685726.9217378368356.7531318711685730.45733997368332.003916671
1685767.93472299368312.204544511 1685729.0430991368247.856584991
     1685715.443      368171.889     1685702.085      368149.625
1685706.10508804368117.605411125     1685668.316      368085.056
     1685662.379      368045.722     1685574.061      367931.428
     1685569.237      367916.9561685577.15394478367896.030509203
1685533.22032616367723.6757066811685483.92150477367659.064834922
1685433.35749285 367544.756272891685404.35317206367524.911127768
     1685387.407      367498.0041685336.05835948367371.468510612
1685289.81707405367313.187040539     1685260.868      367259.769
     1685258.641      367201.1381685244.16899982367184.811000556

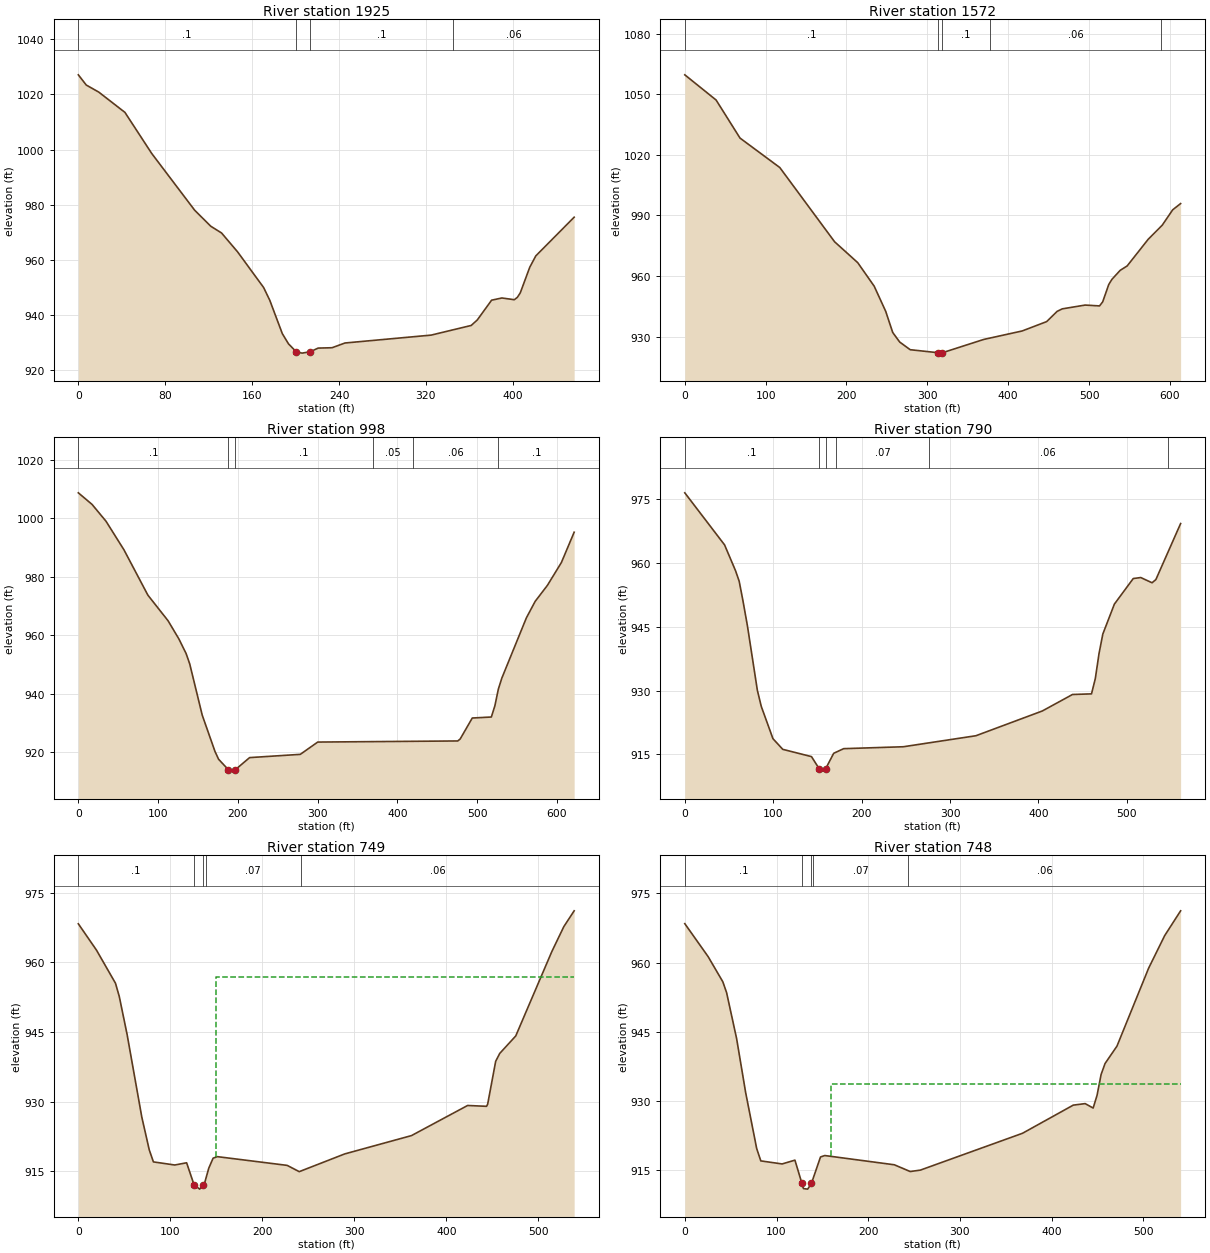
Type RM Length L Ch R = 1 ,1925    ,350.6,353.2,354.8
XS GIS Cut Line= 3
1686159.61140343368589.7854497211685998.19385004368812.456607492
1685880.07069098368950.194744212
#Sta/Elev= 30
       0 1027.14     7.3 1023.43    18.8 1020.87    42.9  1013.5    67.6  998.56
   107.1  977.97   121.9  972.16   131.9  969.69   146.7   962.8   170.6  949.89
   176.3  945.22   187.8  933.15   193.5  929.43  200.55  926.59     206  926.06
   213.6  926.57   220.8  927.89   233.6  928.02   245.5  929.74   324.8   932.6
   361.7  936.11   367.3   938.1   380.5  945.29     390  946.09   401.4  945.46
   404.2  946.32   406.9  947.96   415.6  957.23   421.2  961.38   456.5  975.43
#Mann= 4 ,-1,0
       0      .1       0  200.55    .045       0   213.6      .1       0
  345.02     .06       0
Bank Sta=200.55,213.6
XS Rating Curve= 0 ,0
Exp/Cntr(USF)=0,0
Exp/Cntr=0.3,0.1

Type RM Length L Ch R = 1 ,1572    ,569,573.3,567.8
XS GIS Cut Line= 6
1686096.33010292368380.3767264191686013.02416718368424.860561341
1685933.54893242 368461.642640011685864.24460909368490.312530175
 1685771.8392821368528.5381755081685535.04972942368626.491391674
#Sta/Elev= 30
       0 1059.56    38.7  1047.1    68.3 1028.25   117.5 1013.67   185.3  976.91
   213.9  966.58   234.3  954.91   248.5  942.49   257.2  932.01   265.8  927.29
   278.8  923.48     313922.0067     317  921.79   318.7921.9901   369.7  928.56
   417.3  932.76   447.6  937.39   460.6  942.48     467  943.71   495.2  945.58
     513  945.16   516.9  947.18   524.4  955.75   528.3   958.3   538.5  962.75
   547.2  964.96   573.2  978.16   590.5   985.1   603.5  992.74   613.3  995.83
#Mann= 5 ,-1,0
       0      .1       0     313    .045       0   318.7      .1       0
  377.01     .06       0  589.51      .1       0
Bank Sta=313,318.7
XS Rating Curve= 0 ,0
Exp/Cntr(USF)=0,0
Exp/Cntr=0.3,0.1

Type RM Length L Ch R = 1 ,998     ,208.1,208.2,206.8
XS GIS Cut Line= 6
1685833.25608137367958.0980019781685752.61319804368006.133010885
1685608.06525878368080.3976261381685513.87286187368122.081925979
1685360.08970487368187.4394068031685273.57511411368226.633554137
#Sta/Elev= 30
       0 1008.62    17.2 1004.66    34.7  998.91    57.2  989.14    87.2  973.65
   112.5   964.9   126.1  958.67   135.1  953.69   139.6  950.19   155.3  932.65
   171.3  920.24   175.8  917.59   188.1 913.993   193.7  913.52   196.8  914.01
   214.7  918.14   278.2  919.25   300.1  923.45   475.6  923.83   478.6  924.48
   493.8  931.67   517.7  932.01   522.1  935.81   526.5  941.56   530.8  945.27
   561.6  965.88   572.6  971.52   587.9  976.97   605.5   984.8   621.5  995.16
#Mann= 6 ,-1,0
       0      .1       0   188.1    .045       0   196.8      .1       0
  369.39     .05       0  419.39     .06       0  526.48      .1       0
Bank Sta=188.1,196.8
XS Rating Curve= 0 ,0
Exp/Cntr(USF)=0,0
Exp/Cntr=0.3,0.1

Type RM Length L Ch R = 1 ,790     ,41.7,40.8,40.9
XS GIS Cut Line= 4
1685715.88261205367831.8084622751685608.21406856367857.998107989
1685534.49506581367900.6775306351685194.02967152368031.625759206
#Sta/Elev= 30
       0  976.48      45  964.24    57.4  958.17    61.5  955.71    65.6  951.31
    70.8  945.27    82.1  930.04    86.5  926.28    99.7   918.7   110.8  916.19
   143.3  914.48   151.9911.6613   156.6  911.07   159.3 911.625   168.4  915.26
   179.7  916.35   247.2   916.8   329.3  919.39   404.3   925.2   438.5  929.08
     460  929.23   464.3   932.8   468.5  938.69   472.8  943.29   485.9  950.33
   507.2  956.33   515.7  956.57   528.5  955.34   532.8  956.09   560.8  969.26
#Mann= 6 ,-1,0
       0      .1       0   151.9    .045       0   159.3      .1       0
  170.81     .07       0  275.99     .06       0  545.99      .1       0
Bank Sta=151.9,159.3
XS Rating Curve= 0 ,0
Exp/Cntr(USF)=0,0
Exp/Cntr=0.3,0.1

Type RM Length L Ch R = 1 ,749     ,1.8,1.7,1.6
XS GIS Cut Line= 5
1685684.28704822367801.6253543161685636.29132998 367807.19391831
1685606.85749173367813.5579914461685517.54595568367865.783316599
1685189.86899341368007.471168286
#Sta/Elev= 30
       0  968.28    19.7  962.62    40.4  955.48    44.5  952.64      53  944.47
      69  926.67    77.1  919.62    81.6  917.04   104.8  916.37   117.7  916.85
   125.8912.0924   131.9  911.18   135.4 912.082   137.2  912.46   141.8   915.7
   146.5  917.84   151.1  918.17     227  916.29   240.1  914.94   289.6  918.76
   362.1   922.7   423.1  929.18   443.7     929   444.9  929.47   453.6  938.68
     458  940.38   475.4  944.14   514.7  962.33   527.7  967.68   538.9  971.07
#Mann= 5 ,-1,0
       0      .1       0   125.8    .045       0   135.4      .1       0
  138.43     .07       0  241.89     .06       0
#XS Ineff= 2 , 0
                          150.01          956.91
Permanent Ineff=
       F       F
Bank Sta=125.8,135.4
XS Rating Curve= 0 ,0
Exp/Cntr(USF)=0,0
Exp/Cntr=0.3,0.1

Type RM Length L Ch R = 1 ,748     ,2.1,2.1,2.4
XS GIS Cut Line= 5
1685685.27495599367797.6831352411685636.57361391367804.149703484
1685606.76677619367811.2308369041685517.55824376367864.291033615
1685188.13164909368002.098471662
#Sta/Elev= 30
       0  968.41    25.4  961.29    41.5  955.82    45.6  953.47    56.5  943.54
    66.4  931.81    78.4  919.73    82.9  917.06   106.1   916.4   120.1  917.22
   127.7912.1959   129.4  911.07     134  910.95   138.1  912.19     148  917.91
   152.7  918.22   228.5  916.22   245.8  914.76   256.8  915.06   368.3  923.04
   423.6  929.13   436.6  929.46   445.3   928.5   449.6  931.28     454  935.78
   458.3  938.14   471.3  941.91   505.8  958.77   523.3  965.82   540.7  971.19
#Mann= 5 ,-1,0
       0      .1       0   127.7    .045       0   138.1      .1       0
  139.77     .07       0  243.56     .06       0
#XS Ineff= 2 , 0
                           159.8          933.77
Permanent Ineff=
       F       F
Bank Sta=127.7,138.1
XS Rating Curve= 0 ,0
Exp/Cntr(USF)=0,0
Exp/Cntr=0.3,0.1

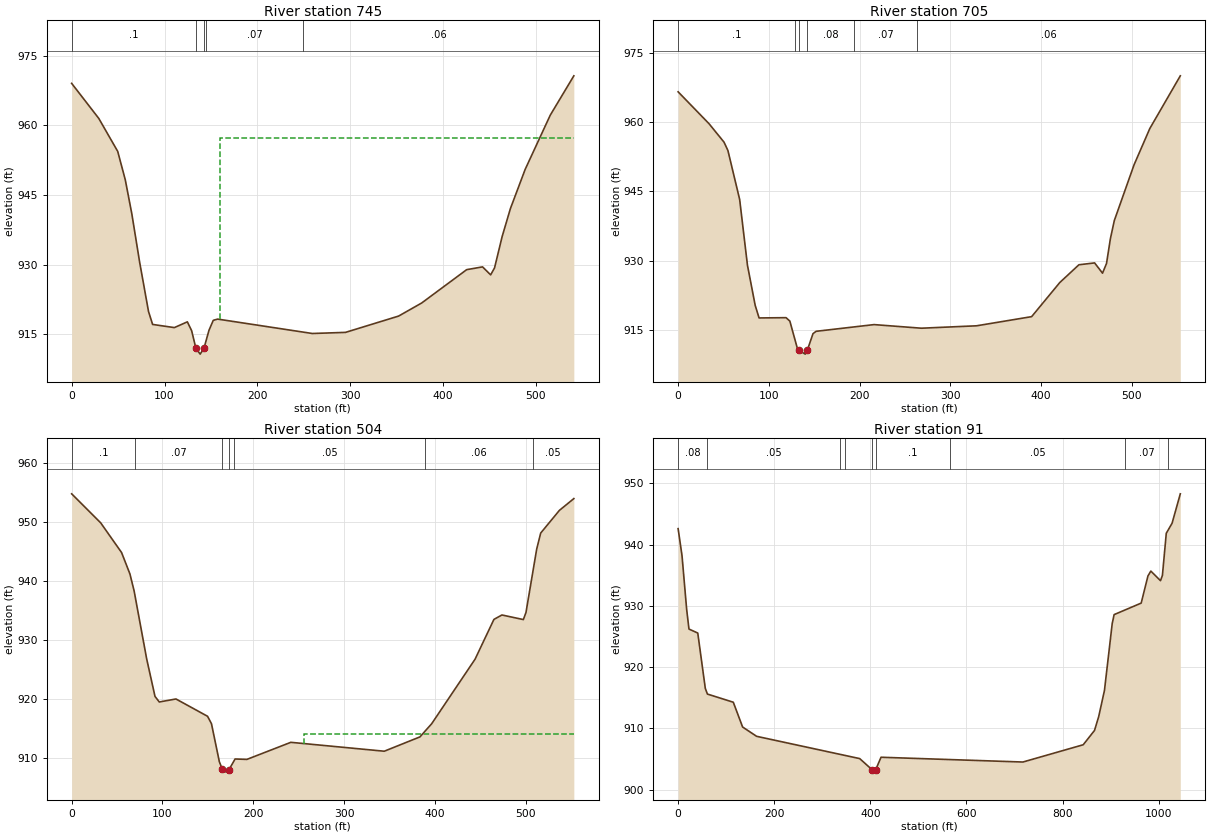
Type RM Length L Ch R = 1 ,745     ,40.4,40.7,42
XS GIS Cut Line= 5
 1685689.1752563367792.4417276661685635.15905211367800.310178589
1685606.00504047367809.0556556881685516.45987987367862.826393468
1685188.39647609367988.432364383
#Sta/Elev= 30
       0  969.01    29.2  961.47    49.6  954.37    57.8  948.22    64.8  940.93
    73.3  930.43    82.8  919.89    87.2  917.12   110.6  916.44   124.6  917.68
   129.2  915.78  133.79  912.01   138.4  910.73   142.5911.9978   147.9  915.86
   152.5     918   157.2  918.27   259.2  915.17   294.9  915.41   352.1  918.92
   376.9  921.73   425.4  928.91   442.5  929.51   451.2  927.79   455.4  929.28
   463.6  936.04   472.5  942.06   488.4   950.5   515.4  962.16   540.8  970.63
#Mann= 5 ,-1,0
       0      .1       0  133.79    .045       0   142.5      .1       0
  145.02     .07       0  249.47     .06       0
#XS Ineff= 2 , 0
                             160           957.2
Permanent Ineff=
       F       F
Bank Sta=133.79,142.5
XS Rating Curve= 0 ,0
Exp/Cntr(USF)=0,0
Exp/Cntr=0.3,0.1

Type RM Length L Ch R = 1 ,705     ,200.5,200.4,199.8
XS GIS Cut Line= 6
1685681.43874844 367755.267684571685636.26508927367764.849975909
 1685605.8070918367776.8278400821685535.30880552367801.810242501
 1685502.5057558367851.6335199751685189.14259234367983.410766333
#Sta/Elev= 30
       0  966.54    34.1  959.63    50.6  955.64    54.9  953.82    67.8  943.25
    76.4  929.01    84.9  920.34    89.2   917.6   118.9  917.66   123.1  916.92
   131.6  910.86     133  910.58   140.1  909.77   142.3910.5729   148.6   914.2
   152.1  914.71   215.9  916.16     268  915.38   328.8   915.9   389.5  917.88
   420.5  925.26   441.6  929.11   458.9  929.51   467.6  927.29     472  929.39
   476.3  934.78   480.6  938.68   502.3  950.72   519.7  958.59   553.3     970
#Mann= 6 ,-1,0
       0      .1       0  128.91     .08       0     133    .045       0
   142.3     .08       0   193.7     .07       0  263.35     .06       0
Bank Sta=133,142.3
XS Rating Curve= 0 ,0
Exp/Cntr(USF)=0,0
Exp/Cntr=0.3,0.1

Type RM Length L Ch R = 1 ,504     ,413.5,413.6,413.1
XS GIS Cut Line= 6
1685619.94780374367657.1857265331685516.24144687367598.185364275
 1685354.3375712367664.608459769 1685284.9341667367693.037536783
1685205.40250163367731.9600311061685122.20253679367778.330017103
#Sta/Elev= 30
       0  954.83      32   949.9      55  944.86    64.2  941.22    68.8  938.35
    82.6  926.83    91.8  920.44    96.5  919.49   114.9     920   149.7  917.06
     154   915.8   162.7  909.33   166.1  908.03   170.3  907.58   173.4 908.025
     180  909.81     193  909.74   241.4  912.64   344.3  911.13   383.6  913.56
   396.5  915.79   444.3  926.75   465.1  933.51   473.9  934.26   497.5  933.48
   500.4  934.69   512.2  945.46   516.6  948.17   537.2  952.02   553.1  954.02
#Mann= 7 ,-1,0
       0      .1       0      70     .07       0   166.1    .045       0
   173.4     .07       0  179.31     .05       0  389.31     .06       0
  507.86     .05       0
#XS Ineff= 2 , 0
                          255.36          914.02
Permanent Ineff=
       F       F
Bank Sta=166.1,173.4
XS Rating Curve= 0 ,0
Exp/Cntr(USF)=0,0
Exp/Cntr=0.3,0.1

Type RM Length L Ch R = 1 ,91      ,,,
XS GIS Cut Line= 4
 1685606.7705867367426.6866813641685329.15744773367236.135651061
1685028.54677061367380.6916050841685064.68575912367753.580259212
#Sta/Elev= 30
       0  942.62     8.1  938.23    17.8  929.41    22.6  926.22    40.9  925.57
    56.6  916.52      61   915.6   114.8  914.27   134.2  910.22   163.3   908.7
   377.8  905.06   403.2903.2745   408.9  902.85   411.2903.2567   422.2  905.28
   717.4   904.5   842.9  907.32   866.4  909.66   875.1  911.92   887.1   916.2
   903.2  927.11   907.2  928.58   963.5  930.46   977.6   934.9   983.6  935.69
  1003.7  934.12  1007.7  934.99  1015.7  941.86  1027.8  943.51  1044.9  948.31
#Mann= 9 ,-1,0
       0     .08       0      60     .05       0  336.72      .1       0
  346.72     .05       0   403.2    .045       0   411.2      .1       0
  566.72     .05       0  930.28     .07       0 1020.28     .05       0
Bank Sta=403.2,411.2
XS Rating Curve= 0 ,0
Exp/Cntr(USF)=0,0
Exp/Cntr=0.3,0.1
LCMann Table=0

Chan Stop Cuts=-1
Use User Specified Reach Order=0
Composite Channel Slope=5